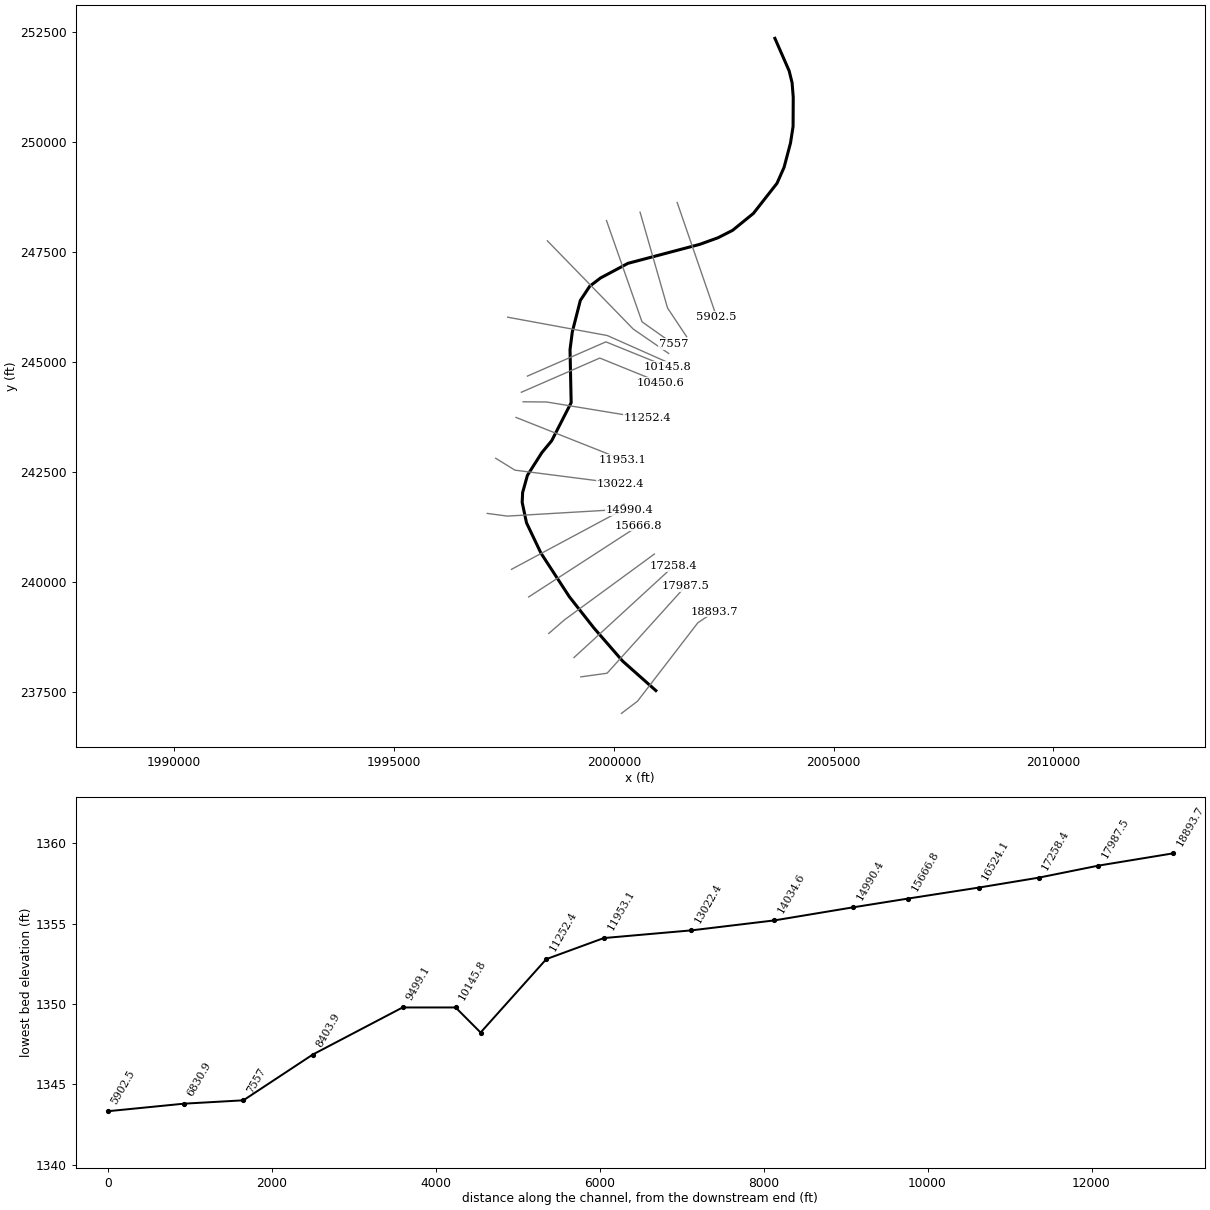
--- NEWRV2_AE.prj (project) ---

Proj Title=NEWRV2_AE
Current Plan=p02
Default Exp/Contr=0,0
English Units
Geom File=g01
Flow File=f01
Flow File=f02
Flow File=f03
Plan File=p01
Plan File=p02
Plan File=p03
BEGIN DESCRIPTION:
Stream Name- New River 2
Kanawha County, WV
WV Disaster Studies / PMR
WVDHSEM-2017-2, Flood Risk Project
HEC-RAS Version: HEC-RAS 4.1
Upstream Extents: 500 ft. downstream of State Route 3(Veterans Memorial Bridge)
Downstream Extents: .9 mi. downstream of State Route 20 (Temple St – Hinton
New River Bridge)
General Notes:  Hydrology- The New River study upstream extent is located at the confluence of New River and Greenbrier River. Approximately 4000ft upstream of the confluence is Bluestone Dam (Nation Inventory of Dams ID: WV08902), which regulates the flows of New River. The Water Control Manual for Bluestone Lake - New River (U.S. Army Corps, 1994) was studied to determine the maximum frequency storm event that Bluestone Dam can handle. A 17C analysis was performed on the nearest gage upstream of the dam, Glen Lyn at New River (gage ID 03178500), and a drainage area weighting equation was applied to project the Glen Lyn flow estimate to the dam location. The dam operations manual cited historic flood events that the dam was designed for, and historic events the dam had successfully conveyed. The discharges from these events were compared to the dam inflow discharge found from the drainage area adjusted Glen Lyn 17C result. This analysis was used to determine that Bluestone Dam is capable of handling up to a 1% frequency storm event. There was not enough evidence to conclude the dam can handle a 0.2% frequency event.
Based off this analysis, the 10%, 4%, 2%, 1% and 1%plus frequency events were estimated using a 17C analysis of post-regulation peakflows. On the study reach, downstream of the New River and Greenbrier River confluence, is the gage Hinton at New River (gage ID 03184500). A bulletin 17C EMA analysis was performed on this gage using the period of peakflow record after the implementation of Bluestone Dam. The discharges up to the 1%plus frequency event were estimated using the dam-regulated peakflows. For the 17C EMA analyses at the Glen Lyn gage and at the Hinton gage, weighted skews were comprised of the gage skew and the United States (US) skew and US Mean Square Error (MSE). The 0.2% frequency event discharge was taken directly from the USGS Scientific Investigations Report 2010-5033, table 3, Qs result. The SIR2010-5033 report only considers unregulated peakflow values when estimating discharges at a gage using Bulletin 17B.
END DESCRIPTION:
DSS File=dss
DSS Export Rating Curves= 0
DSS Export Rating Curve Sorted= 0
DSS Export Volume Flow Curves= 0
DXF OffsetX= 0
DXF OffsetY= 0
DXF ScaleX= 0
DXF ScaleY= 0

--- NEWRV2_AE.p02 (plan) ---

Plan Title=Mulitprofile
Program Version=5.07
Short Identifier=multip
Geom File=g01
Flow File=f02
Subcritical Flow
K Sum by GR= 0
Std Step Tol= 0.01
Critical Tol= 0.01
Num of Std Step Trials= 20
Max Error Tol= 0.3
Flow Tol Ratio= 0.001
Split Flow NTrial= 30
Split Flow Tol= 0.02
Split Flow Ratio= 0.02
Log Output Level= 0
Friction Slope Method= 1
Unsteady Friction Slope Method= 2
Unsteady Bridges Friction Slope Method= 1
Parabolic Critical Depth
Global Vel Dist= 0 , 0 , 0
Global Log Level= 0
CheckData=True
Encroach Param=-1 ,0,0, 0
Mapping Interval=1HOUR
Computation Time Step Use Courant=        0
Computation Time Step Use Time Series=    0
Computation Time Step Count To Double=0
Computation Time Step Max Doubling=0
Computation Time Step Max Halving=0
Computation Time Step Residence Courant=0
Run HTab= 0
Run UNet= 0
Run Sediment= 0
Run PostProcess= 0
Run WQNet= 0
Run RASMapper= 0
UNET Theta= 0
UNET Theta Warmup= 0
UNET ZTol= 0
UNET ZSATol= 0
UNET MxIter= 0
UNET Max Iter WO Improvement= 0
UNET MaxInSteps= 0
UNET DtIC= 0
UNET DtMin= 0
UNET MaxCRTS= 0
UNET WFStab= 0
UNET SFStab= 0
UNET WFX= 1
UNET SFX= 1
UNET 1D Methodology=Finite Difference
UNET DSS MLevel= 1
UNET Pardiso=0
UNET DZMax Abort= 0
UNET Use Existing IB Tables= 0
UNET Froude Reduction=False
UNET Froude Limit= 0
UNET Froude Power= 0
UNET D1 Cores= 0
UNET D2 Coriolis=0
UNET D2 Cores= 0
UNET D2 Theta= 1
UNET D2 Theta Warmup= 1
UNET D2 Z Tol= 0.01
UNET D2 Volume Tol= 0.01
UNET D2 Max Iterations= 20
UNET D2 Equation= 0
UNET D2 RampUpFraction=0.1
UNET D2 TimeSlices= 1
UNET D2 BCVolumeCheck=0
UNET D1D2 MaxIter= 0
UNET D1D2 ZTol=0.01
UNET D1D2 QTol=0.1
UNET D1D2 MinQTol=1
Write IC File= 0
Write IC File at Fixed DateTime=0
Write IC File at Sim End=0
Echo Input=False
Echo Parameters=False
Echo Output=False
Write Detailed= 0
HDF Write Warmup=0
HDF Write Time Slices=0
HDF Flush=0
HDF Face Node Velocities=0
HDF Compression= 1
HDF Chunk Size= 1
HDF Spatial Parts= 1
HDF Use Max Rows=0
HDF Fixed Rows= 1
Calibration Method= 0
Calibration Iterations= 20
Calibration Max Change=0.05
Calibration Tolerance=0.2
Calibration Maximum=1.5
Calibration Minimum=0.5
Calibration Optimization Method= 1
WQ AD Non Conservative
WQ ULTIMATE=-1
WQ Max Comp Step=1HOUR
WQ Output Interval=15MIN
WQ Output Selected Increments= 0
WQ Output face flow=0
WQ Output face velocity=0
WQ Output face area=0
WQ Output face dispersion=0
WQ Output cell volume=0
WQ Output cell surface area=0
WQ Output cell continuity=0
WQ Output cumulative cell continuity=0
WQ Output face conc=0
WQ Output face dconc_dx=0
WQ Output face courant=0
WQ Output face peclet=0
WQ Output face adv mass=0
WQ Output face disp mass=0
WQ Output cell mass=0
WQ Output cell source sink temp=0
WQ Output nsm pathways=0
WQ Output nsm derived pathways=0
WQ Output MaxMinRange=-1
WQ Daily Max Min Mean=-1
WQ Daily Range=0
WQ Daily Time=0
WQ Create Restart=0
WQ Fixed Restart=0
WQ System Summary=0
WQ Write To DSS=0
WQ Use Fixed Temperature=0
Sorting and Armoring Iterations= 10
XS Update Threshold= 0.02
Bed Roughness Predictor= 0
Hydraulics Update Threshold= 0.02
Energy Slope Method= 1
Volume Change Method= 0
Sediment Retention Method= 0
XS Weighting Method= 0
Number of US Weighted Cross Sections= 1
Number of DS Weighted Cross Sections= 1
Upstream XS Weight=0.25
Main XS Weight=0.5
Downstream XS Weight=0.25
Number of DS XS's Weighted with US Boundary= 1
Upstream Boundary Weight= 1
Weight of XSs Associated with US Boundary= 0
Number of US XS's Weighted with DS Boundary= 1
Downstream Boundary Weight= 0.5
Weight of XSs Associated with DS Boundary= 0.5
Percentile Method= 0
Sediment Output Level= 4
Mass or Volume Output= 0
Output Increment Type= 1
Profile and TS Output Increment= 10
XS Output Flag= 0
XS Output Increment= 10
Write Gradation File= 0
Read Gradation Hotstart= 0
Write HDF5 File= 1
Write Binary Output= 1
Write DSS Sediment File= 0
SV Curve= 0
Specific Gage Flag= 0

--- NEWRV2_AE.p01 (plan) ---

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Plan Title=June16 Disaster
Program Version=4.10
Geom File=g01
Flow File=f01
UNET Convert EG Bridges= 0
UNET Time Slicing=0,0, 5
UNET Junction Losses=0
DSS File=dss
WQ Output cell source sink nsm=0
Disregard all LS=0
Disregard all Conn=0
Disregard all Breaches=0
Disregard all Pumps=0

--- NEWRV2_AE.p03 (plan) ---

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Plan Title=Floodway
Program Version=4.10
Short Identifier=Floodway
Geom File=g01
Flow File=f03
Encroach Param=-1 ,0,0, 2
Encroach River=NEWRV
Encroach Reach=Main
Encroach Node=18893.7
       1     546  2091.2
Encroach Node=17987.5
       1   753.9  2128.6
Encroach Node=17258.4
       1  467.61  1810.8
Encroach Node=16524.1
       1   558.1  1888.5
Encroach Node=15666.8
       1   436.2 1727.95
Encroach Node=14990.4
       1   449.4  1741.9
Encroach Node=14034.6
       1     675  1781.2
Encroach Node=13022.4
       1   631.4  1565.7
Encroach Node=11953.1
       1  670.09    1327
Encroach Node=11252.4
       1  670.69  1532.6
Encroach Node=10450.6
       1   737.4  1725.6
Encroach Node=10145.8
       1   566.7 1558.93
Encroach Node=9499.1
       1  1120.7    1953
Encroach Node=8403.9
       1  1045.6  1858.5
Encroach Node=7557
       1   743.8  1464.7
Encroach Node=6830.9
       1     679  1436.8
Encroach Node=5902.5
       1   596.7  1544.2
Encroach Node=4864.6
       1   592.8  1552.5
Encroach Node=3820.1
       1     544  1463.1
Encroach Node=3129.3
       1   432.2  1415.6
Encroach Node=2529.4
       1   447.7  1448.2
Encroach Node=1795.8
       1   577.1  1610.8
Encroach Node=936.4
       1     743  1664.6
Encroach Node=103.2
       1  1053.9  1838.6
UNET Convert EG Bridges= 0
UNET Time Slicing=0,0, 5
UNET Junction Losses=0
DSS File=dss
WQ Output cell source sink nsm=0
Disregard all LS=0
Disregard all Conn=0
Disregard all Breaches=0
Disregard all Pumps=0

--- NEWRV2_AE.f02 (steady flow) ---

Flow Title=Regulated Flows at Hinton Gage
Program Version=5.07
Number of Profiles= 6
Profile Names=P100yr,P10yr,P25yr,P50yr,P100yrPLUS,P500yr
River Rch & RM=NEWRV,Main            ,18893.7
   87057   72176   78552   82932   93166  365000
Boundary for River Rch & Prof#=NEWRV,Main            , 1
Up Type= 0
Dn Type= 1
Dn Known WS=1345.7
Boundary for River Rch & Prof#=NEWRV,Main            , 2
Up Type= 0
Dn Type= 1
Dn Known WS=1344.1
Boundary for River Rch & Prof#=NEWRV,Main            , 3
Up Type= 0
Dn Type= 1
Dn Known WS=1344.8
Boundary for River Rch & Prof#=NEWRV,Main            , 4
Up Type= 0
Dn Type= 1
Dn Known WS=1345.3
Boundary for River Rch & Prof#=NEWRV,Main            , 5
Up Type= 0
Dn Type= 1
Dn Known WS=1346.5
Boundary for River Rch & Prof#=NEWRV,Main            , 6
Up Type= 0
Dn Type= 1
Dn Known WS=1363.9
DSS Import GetInterval= 0
DSS Import GetPeak= 0
DSS Import FillOption= 0

--- NEWRV2_AE.f01 (steady flow) ---

Flow Title=June16
Program Version=4.10
Number of Profiles= 1
Profile Names=June16
River Rch & RM=NEWRV,Main            ,18893.7
   85100
Boundary for River Rch & Prof#=NEWRV,Main            , 1
Up Type= 0
Dn Type= 3
Dn Slope=0.005
Observed WS=NEWRV           ,Main            ,18893.7 ,0,1372.4
Observed WS=NEWRV           ,Main            ,17258.4 ,0,1370.8
Observed WS=NEWRV           ,Main            ,15666.8 ,0,1369.3
Observed WS=NEWRV           ,Main            ,13022.4 ,0,1366.9
Observed WS=NEWRV           ,Main            ,11953.1 ,700,1365.3
Observed WS=NEWRV           ,Main            ,11252.4 ,231,1364.61
Observed WS=NEWRV           ,Main            ,9499.1  ,0,1361.4
Observed WS=NEWRV           ,Main            ,6830.9  ,0,1356.8
Observed WS=NEWRV           ,Main            ,5902.5  ,0,1355.9
Observed WS=NEWRV           ,Main            ,3820.1  ,0,1351.6
Observed WS=NEWRV           ,Main            ,3129.3  ,0,1350.4
Observed WS=NEWRV           ,Main            ,2529.4  ,0,1347.8
Observed WS=NEWRV           ,Main            ,1795.8  ,0,1346.1
DSS Import GetInterval= 0
DSS Import GetPeak= 0
DSS Import FillOption= 0

--- NEWRV2_AE.f03 (steady flow) ---

Flow Title=Floodway
Program Version=5.07
Number of Profiles= 2
Profile Names=P100yr,Floodway
River Rch & RM=NEWRV,Main            ,18893.7
   87057   87057
Boundary for River Rch & Prof#=NEWRV,Main            , 1
Up Type= 0
Dn Type= 1
Dn Known WS=1345.7
Boundary for River Rch & Prof#=NEWRV,Main            , 2
Up Type= 0
Dn Type= 1
Dn Known WS=1345.8
Observed WS=NEWRV           ,Main            ,18893.7 ,0,1372.4,
Observed WS=NEWRV           ,Main            ,17258.4 ,0,1370.8,
Observed WS=NEWRV           ,Main            ,15666.8 ,0,1369.3,
Observed WS=NEWRV           ,Main            ,13022.4 ,0,1366.9,
Observed WS=NEWRV           ,Main            ,11252.4 ,0,1365.3,
Observed WS=NEWRV           ,Main            ,9499.1  ,0,1361.4,
Observed WS=NEWRV           ,Main            ,6830.9  ,0,1356.8,
Observed WS=NEWRV           ,Main            ,5902.5  ,0,1355.9,
Observed WS=NEWRV           ,Main            ,3820.1  ,0,1351.6,
Observed WS=NEWRV           ,Main            ,3129.3  ,0,1350.4,
Observed WS=NEWRV           ,Main            ,2529.4  ,0,1347.8,
Observed WS=NEWRV           ,Main            ,1795.8  ,0,1346.1,
DSS Import GetInterval= 0
DSS Import GetPeak= 0
DSS Import FillOption= 0

--- NEWRV2_AE.g01 (geometry) ---

Geom Title=USGS 1m DEM
Program Version=5.07

River Reach=NEWRV           ,Main
Reach XY= 30
     2000956.789      237520.738     2000201.571      238190.534
     1999545.321      238945.742     1998988.344      239653.791
     1998343.798      240642.676     1998013.406       241335.25
     1997915.112      241799.909     1997925.529      242023.867
     1998034.904      242414.492     1998363.029      242930.117
     1998586.987      243200.951     1999029.696      244065.534
     1999003.654      245268.659     1999055.737      245674.909
     1999238.029      246388.451     1999451.571      246711.367
     1999696.362      246898.867     2000321.362      247232.201
     2001956.779      247664.492     2002370.843      247814.232
     2002701.571      247982.201     2003175.529      248367.617
     2003711.913      249051.335     2003873.446      249414.492
     2004019.279      249966.576     2004078.291      250344.391
     2004081.779      251008.242     2004055.737      251336.367
     2003988.727      251607.044     2003664.657       252346.74

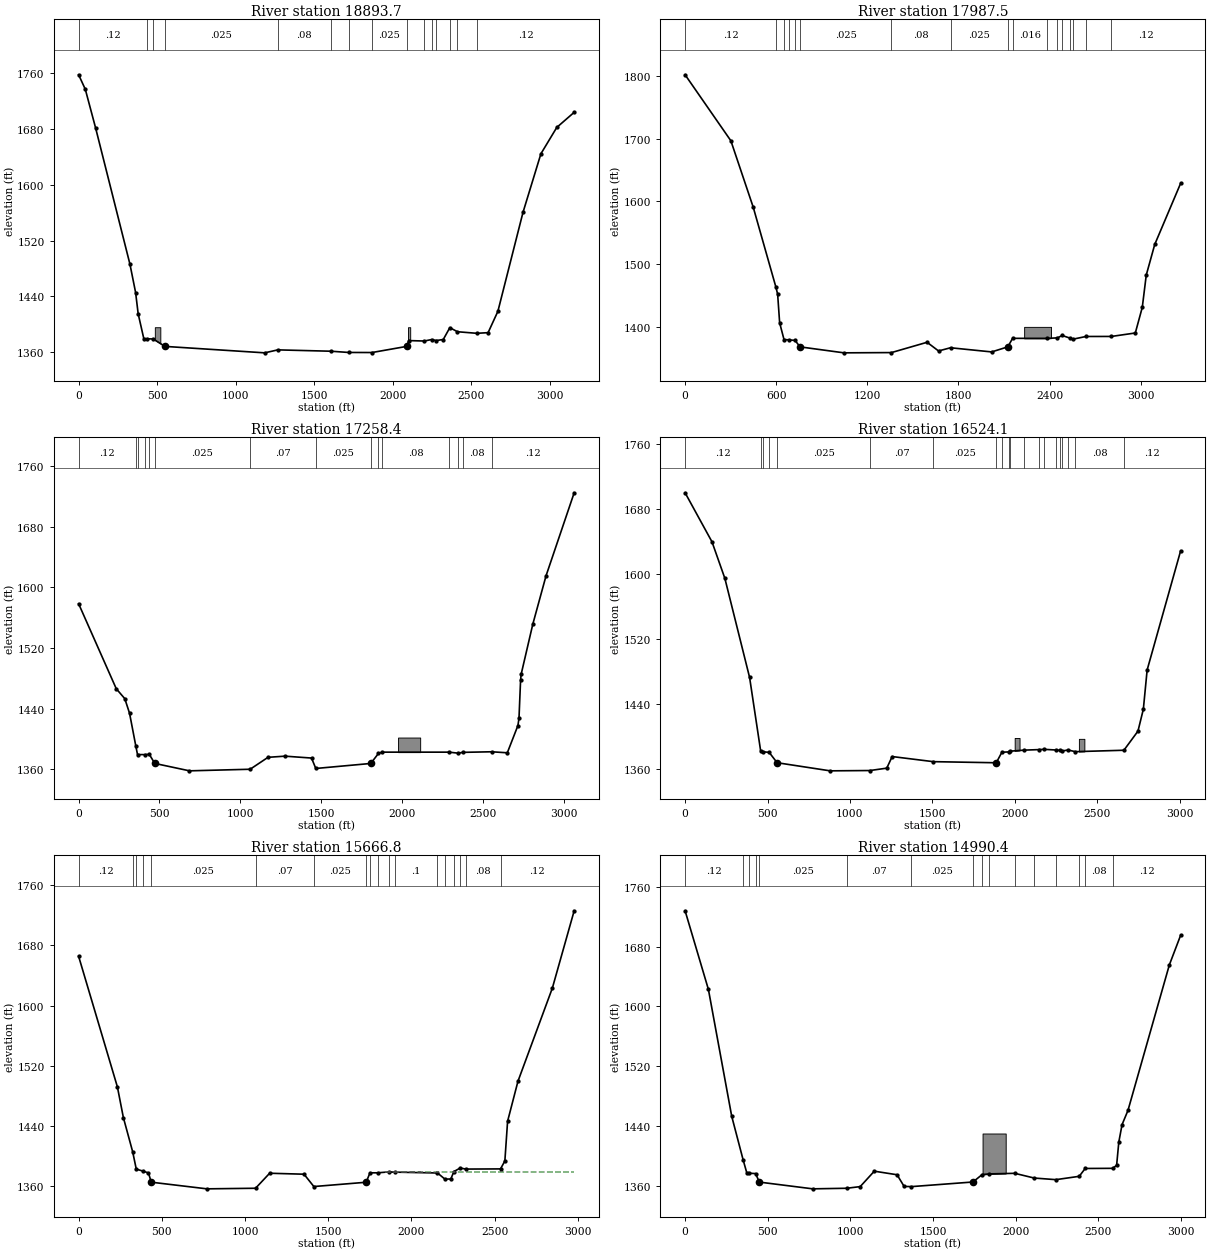
Type RM Length L Ch R = 1 ,18893.7 ,936.9,906.1,841.5
Node Name=V
XS GIS Cut Line= 4
     2000173.793      237003.034     2000538.415       237279.23
     2001911.616      239062.341     2002282.242      239310.789
#Sta/Elev= 30
       0 1756.98    42.5  1736.2   107.8 1681.15   326.7 1486.04   362.7 1445.56
     379 1415.18     415 1379.53   433.8 1379.48     475 1379.19   549.3 1368.58
  1184.4 1359.37  1267.8 1363.61  1605.1 1361.69  1718.4 1359.92  1867.1 1359.81
 2089.05 1368.62  2101.1  1376.9  2200.3 1376.26  2246.5 1378.38  2275.5 1376.95
  2320.9 1378.42  2362.7 1395.37  2411.4 1389.55  2533.9 1387.31  2606.3 1388.21
  2668.6 1418.71  2828.5 1560.28  2942.5 1644.04  3043.5  1681.7  3154.2  1703.3
#Mann= 15 ,-1 , 0
       0     .12       0   433.8    .016       0     475     .12       0
   549.3    .025       0  1267.8     .08       0  1605.1    .025       0
  1718.4     .08       0  1867.1    .025       0 2089.05     .08       0
  2200.3    .016       0  2246.5     .06       0  2275.5     .12       0
  2362.7     .06       0  2411.4     .08       0  2533.9     .12       0
#Block Obstruct= 2 ,-1
     485     520    1396  2096.4 2110.52    1396
Bank Sta=549.3,2089.05
XS Rating Curve= 0 ,0
Exp/Cntr=0.3,0.1

Type RM Length L Ch R = 1 ,17987.5 ,759.4,729.1,628.1
XS GIS Cut Line= 3
     1999249.603      237832.856     1999846.864      237915.688
     2001629.927      239890.572
#Sta/Elev= 30
       0 1801.82   301.5 1696.62     449 1590.52   597.7  1463.7   609.5 1452.14
   622.7 1406.46   651.4 1379.83   684.5 1379.26   724.3  1378.4   757.2 1368.11
  1046.4 1358.61    1359 1359.02  1593.8 1375.44  1669.2 1361.61    1748 1366.71
    2019 1360.07  2125.3 1368.14    2157 1381.71  2384.8 1381.69  2452.1 1382.45
  2483.7 1386.26  2532.4 1382.28  2554.9  1380.4  2640.4 1384.68  2807.7 1384.74
  2965.2 1390.25  3011.1 1431.14  3037.3 1482.59  3093.1 1531.35  3263.7  1628.8
#Mann= 17 ,-1 , 0
       0     .12       0   597.7     .06       0   651.4    .016       0
   684.5     .08       0   724.3     .12       0   757.2    .025       0
    1359     .08       0    1748    .025       0  2125.3     .08       0
    2157    .016       0  2384.8     .12       0  2452.1     .06       0
  2483.7     .12       0  2532.4     .06       0  2554.9     .04       0
  2640.4     .08       0  2807.7     .12       0
#Block Obstruct= 1 ,-1
    2233    2410    1400
Bank Sta=757.2,2125.3
XS Rating Curve= 0 ,0
Exp/Cntr=0.3,0.1

Type RM Length L Ch R = 1 ,17258.4 ,772.1,734.3,621.8
XS GIS Cut Line= 2
     1999094.009      238271.861     2001352.265      240342.656
#Sta/Elev= 30
       0 1578.17   232.9 1466.04   285.4 1453.05   314.9 1433.74     354 1390.13
   364.1 1379.33   413.3 1379.24   436.6 1379.71  470.89 1367.63   685.5 1357.86
  1060.5 1359.96  1171.1  1375.7  1276.1 1377.21  1440.1 1374.72  1466.4 1360.98
  1806.4 1367.59    1854 1380.86  1876.4 1382.51  2289.8  1382.5  2347.5 1381.16
  2375.1 1382.24  2553.5    1383  2650.6 1381.66  2716.2 1417.59  2722.8 1427.24
  2732.6 1477.26  2735.9 1484.94  2808.1 1551.15  2890.1 1615.09    3064 1724.53
#Mann= 15 ,-1 , 0
       0     .12       0     354     .06       0   364.1    .016       0
   413.3     .08       0   436.6     .06       0  470.89    .025       0
  1060.5     .07       0  1466.4    .025       0  1806.4    .016       0
    1854     .06       0  1876.4     .08       0  2289.8     .12       0
  2347.5     .06       0  2375.1     .08       0  2553.5     .12       0
#Block Obstruct= 1 ,-1
 1975.07 2111.821401.773
Bank Sta=470.89,1806.4
XS Rating Curve= 0 ,0
Exp/Cntr=0.3,0.1

Type RM Length L Ch R = 1 ,16524.1 ,876.5,857.3,805.9
XS GIS Cut Line= 3
     1998520.012      238819.508     1998877.497      239129.037
     2000922.134      240624.369
#Sta/Elev= 30
       0 1699.95   163.1 1639.51   241.3  1594.4   391.3  1472.3   458.2 1381.96
   471.5 1380.74   509.9 1380.03   558.1 1367.25   879.9 1357.24  1121.2 1357.62
  1223.3 1360.54  1256.1 1374.85  1505.1 1368.56 1887.47 1367.19  1921.7 1380.17
  1962.1 1380.58  1972.5 1381.49  2055.8 1382.75  2145.2  1383.4  2177.8 1383.74
    2251  1382.9  2272.8 1382.48  2287.6 1381.78  2324.2 1382.91  2366.8 1380.87
  2661.8 1382.62  2747.1 1406.17  2779.8 1433.22  2802.8 1481.56    3006 1628.42
#Mann= 20 ,-1 , 0
       0     .12       0   458.2     .06       0   471.5    .016       0
   509.9     .12       0   558.1    .025       0  1121.2     .07       0
  1505.1    .025       0 1887.47     .06       0  1921.7    .016       0
  1962.1     .06       0  1972.5     .08       0  2055.8     .12       0
  2145.2     .08       0  2177.8     .06       0    2251     .08       0
  2272.8     .06       0  2287.6     .08       0  2324.2    .016       0
  2366.8     .08       0  2661.8     .12       0
#Block Obstruct= 2 ,-1
 1999.33 2028.811397.771 2388.86 2422.031396.666
Bank Sta=558.1,1887.47
XS Rating Curve= 0 ,0
Exp/Cntr=0.3,0.1

Type RM Length L Ch R = 1 ,15666.8 ,703.5,676.4,595.7
XS GIS Cut Line= 2
     1998062.682      239648.868     2000562.682      241266.923
#Sta/Elev= 30
       0 1665.57   232.9 1492.08   268.9 1451.25   324.7 1405.86   346.4 1382.77
   387.3 1380.09   419.8 1377.69   436.2 1365.41   770.7 1356.56  1063.2 1357.34
  1147.9 1377.29  1354.5 1376.01  1413.5 1359.61 1727.95 1365.32  1750.8 1377.86
  1797.1 1377.85  1862.4 1379.04    1901 1378.75  2156.5 1377.64    2201  1369.5
  2236.7 1369.62  2255.1 1379.56  2293.2 1384.23  2326.1 1382.83  2535.2 1383.05
  2561.4 1393.62  2577.8 1446.38  2640.1 1499.53  2846.8 1623.36  2977.9 1726.14
#Mann= 18 ,-1 , 0
       0     .12       0   324.7     .06       0   346.4    .016       0
   387.3      .1       0   436.2    .025       0  1063.2     .07       0
  1413.5    .025       0 1727.95      .1       0  1750.8    .016       0
  1797.1     .08       0  1862.4    .016       0    1901      .1       0
  2156.5     .12       0    2201     .07       0  2255.1     .12       0
  2293.2    .016       0  2326.1     .08       0  2535.2     .12       0
#XS Ineff= 2 , 0
                          1839.9          1378.9
Permanent Ineff=
       F       F
Bank Sta=436.2,1727.95
XS Rating Curve= 0 ,0
Exp/Cntr=0.3,0.1

Type RM Length L Ch R = 1 ,14990.4 ,1050.6,955.9,562.4
XS GIS Cut Line= 3
     1997672.095      240277.146     2000008.824      241528.342
      2000344.51      241619.893
#Sta/Elev= 30
       0 1727.78   141.1  1622.6   282.1    1453     351 1394.88     374 1376.87
   387.1 1376.89   426.5 1376.42   449.4 1365.02   772.6 1356.01   977.6 1356.78
  1059.6 1358.99  1144.9 1379.62  1282.7 1374.84  1325.3 1359.25  1369.3 1358.97
  1741.9 1365.16  1797.7 1375.12  1840.3 1375.97  1994.5 1376.77  2112.9 1370.43
  2243.8 1368.29  2384.9 1372.75    2421 1383.24  2588.3 1383.43  2611.3 1387.62
  2624.4 1418.47  2644.1 1441.83  2679.9 1460.86  2930.3 1655.43  2998.6 1695.03
#Mann= 16 ,-1 , 0
       0     .12       0     351     .06       0   387.1    .016       0
   426.5     .12       0   449.4    .025       0   977.6     .07       0
  1369.3    .025       0  1741.9    .016       0  1797.7     .12       0
  1840.3    .016       0  1994.5     .06       0  2112.9     .12       0
  2243.8     .08       0  2384.9    .016       0    2421     .08       0
  2588.3     .12       0
#XS Ineff= 2 , 0
                            1940         1376.46
Permanent Ineff=
       F       F
#Block Obstruct= 1 ,-1
    1800    1940    1430
Bank Sta=449.4,1741.9
XS Rating Curve= 0 ,0
Exp/Cntr=0.3,0.1

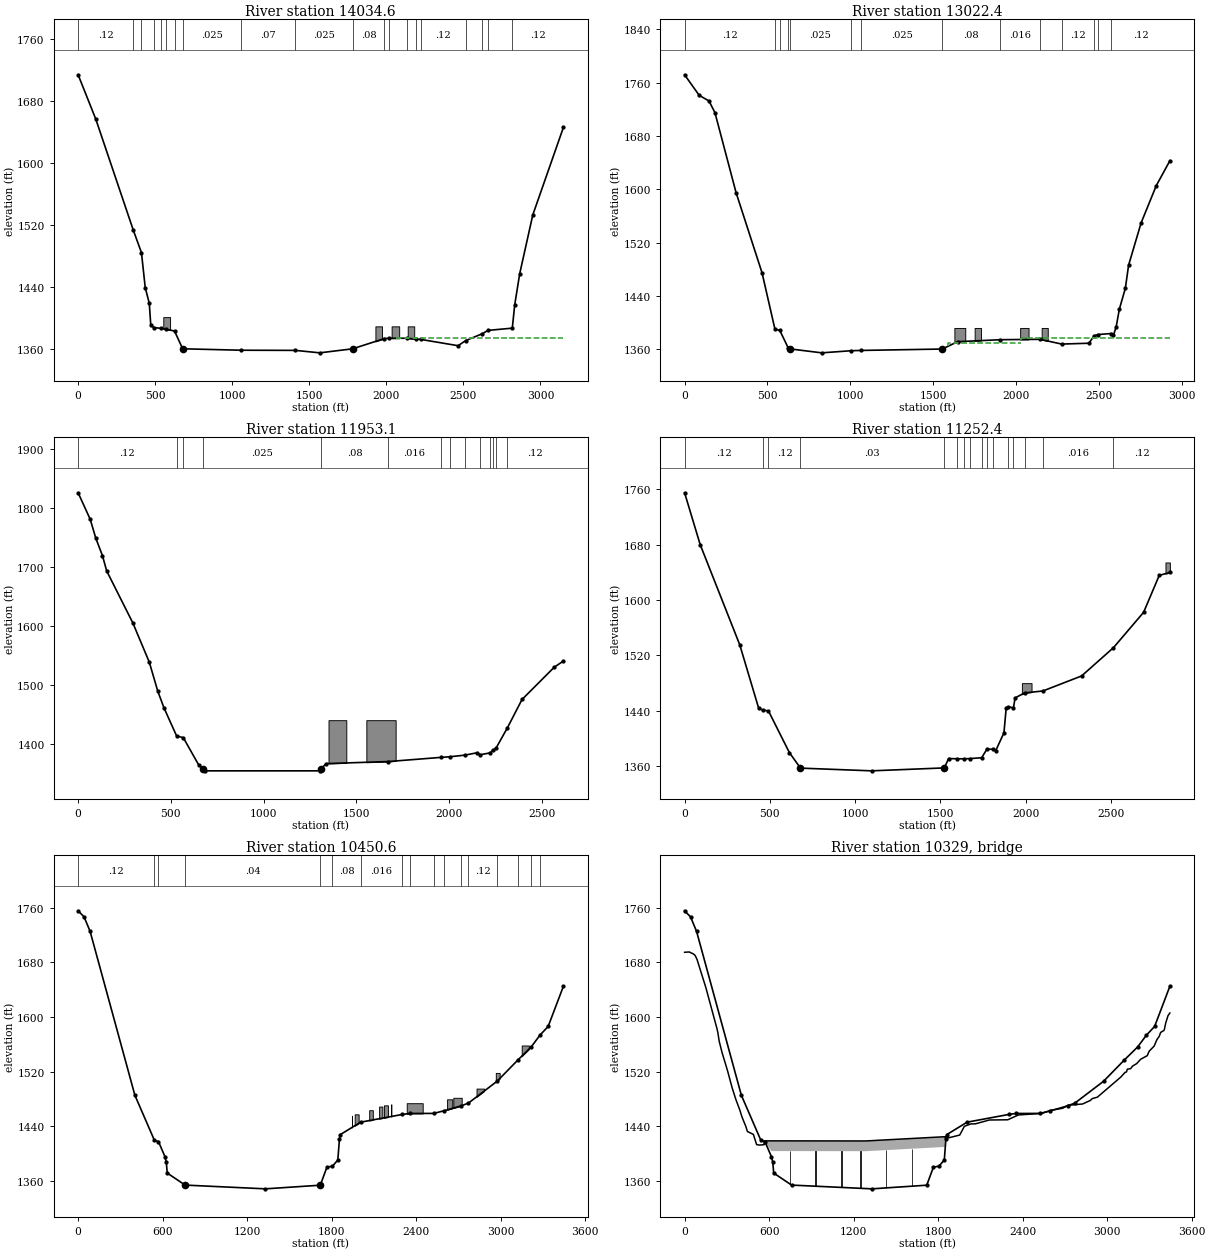
Type RM Length L Ch R = 1 ,14034.6 ,1035.4,1012.2,848.3
Node Name=U
XS GIS Cut Line= 4
     1997121.015      241548.019      1997578.77      241486.985
     1999946.015      241626.491     2000233.746      241757.278
#Sta/Elev= 30
       0 1713.82   114.6 1656.67   357.6 1513.67     411 1484.43   435.6 1439.18
   461.8 1419.17   471.6 1390.63   491.8 1387.81   537.5 1386.82   567.1 1385.76
   625.6 1383.35   678.3 1360.43  1058.7 1358.57  1409.7 1358.37  1568.1  1355.2
  1781.2 1360.39  1987.4 1373.62    2017 1373.98  2135.3 1374.04  2194.5 1372.84
  2224.1 1372.52  2465.8  1364.4  2514.8 1370.95  2623.5 1379.95  2660.3 1384.17
  2817.6 1387.04  2833.2 1417.11  2865.7 1457.36  2950.5 1533.06  3149.2 1645.95
#Mann= 20 ,-1 , 0
       0     .12       0   357.6    .016       0     411     .08       0
   491.8    .016       0   537.5     .08       0   567.1     .06       0
   625.6     .12       0   678.3    .025       0  1058.7     .07       0
  1409.7    .025       0  1781.2     .08       0  1987.4    .016       0
    2017     .12       0  2135.3     .08       0  2194.5    .016       0
  2224.1     .12       0  2514.8     .08       0  2623.5    .016       0
  2660.3     .08       0  2817.6     .12       0
#XS Ineff= 2 , 0
                          2062.4         1374.82
Permanent Ineff=
       F       F
#Block Obstruct= 4 ,-1
  552.75  596.761401.273 1929.25  1972.11389.366 2034.44 2083.441389.366
 2138.86 2181.111389.366
Bank Sta=678.3,1781.2
XS Rating Curve= 0 ,0
Exp/Cntr=0.3,0.1

Type RM Length L Ch R = 1 ,13022.4 ,1100.9,1069.3,875.9
XS GIS Cut Line= 3
     1997312.682      242801.645     1997749.402       242531.76
     2000146.015      242225.256
#Sta/Elev= 30
       0 1771.92    88.3 1741.04   147.2 1732.62   183.1 1715.25   310.6  1595.2
   467.6 1474.68   545.8 1389.68     574 1388.58   624.8 1362.36   634.7 1360.53
  827.68 1354.58  1005.1 1357.73  1063.5 1358.18  1555.9  1360.3  1647.7 1371.32
  1906.4 1374.29  2145.3 1374.87  2276.5 1367.74    2441    1369  2472.2 1380.14
  2495.6 1382.03  2575.4  1383.6  2588.6 1380.81    2605 1393.14  2624.6 1420.18
  2660.7 1451.44  2680.4 1486.24  2755.8 1549.56  2847.6 1605.63  2929.5 1642.88
#Mann= 14 ,-1 , 0
       0     .12       0   545.8    .016       0     574     .08       0
   624.8    .025       0   634.7    .025       0  1005.1     .06       0
  1063.5    .025       0  1555.9     .08       0  1906.4    .016       0
  2145.3     .06       0  2276.5     .12       0  2472.2    .016       0
  2495.6     .08       0  2575.4     .12       0
#XS Ineff= 2 ,-1
  1588.7  2029.1 1368.67  2029.1  2929.5  1376.9
Permanent Ineff=
       F       F
#Block Obstruct= 4 ,-1
 1628.68 1694.351391.955 1750.97  1789.21391.955 2025.61 2076.391391.955
 2155.57 2192.261391.955
Bank Sta=634.7,1555.9
XS Rating Curve= 0 ,0
Exp/Cntr=0.3,0.1

Type RM Length L Ch R = 1 ,11953.1 ,613.4,700.7,816
XS GIS Cut Line= 2
     1997774.796      243730.001     2000207.435      242766.537
#Sta/Elev= 30
       0 1825.66    65.6  1780.4    95.1 1748.81   131.2 1719.09   154.1 1693.05
   295.1 1604.88   383.6 1538.52   429.5 1489.22   462.3 1461.38   531.2 1413.15
   567.2 1410.36   649.2 1364.61   672.2 1357.87  684.14  1354.1    1305  1354.1
 1309.78 1357.79  1337.8 1366.38  1672.2 1369.85  1954.2 1376.87  2003.4 1377.94
  2085.3 1380.71  2150.9 1384.75  2167.3  1381.4  2219.8 1384.42  2239.4 1389.51
  2252.5 1392.16  2314.8 1427.24  2393.5 1475.18  2567.3 1529.87  2616.5 1540.34
#Mann= 14 ,-1 , 0
       0     .12       0   531.2    .016       0   567.2      .1       0
   672.2    .025       0 1309.78     .08       0  1672.2    .016       0
  1954.2     .08       0  2003.4    .016       0  2085.3     .08       0
  2167.3     .06       0  2219.8     .12       0  2239.4    .016       0
  2252.5     .08       0  2314.8     .12       0
#Block Obstruct= 2 ,-1
    1350    1446    1440    1554    1712    1440
Bank Sta=672.2,1309.78
XS Rating Curve= 0 ,0
Exp/Cntr=0.3,0.1

Type RM Length L Ch R = 1 ,11252.4 ,537.2,801.9,1094
Node Name=T
XS GIS Cut Line= 3
       1997936.1      244085.248     1998472.327      244080.889
     2000752.381      243705.966
#Sta/Elev= 30
       0 1755.13    91.6 1680.08   323.7 1535.13   434.9 1443.16   457.8 1440.85
   492.1 1439.43   614.9 1379.15  679.96 1356.73 1096.83 1352.79 1523.21 1357.03
    1549 1370.53  1598.2 1370.26  1637.5 1370.19  1674.2 1370.49  1742.8 1371.78
  1772.7 1383.81  1807.9 1384.24  1824.3 1381.47  1873.5 1407.78  1886.6 1443.62
  1899.4 1445.44  1929.2 1443.94    1939 1458.37  1994.8 1465.55    2102 1468.35
  2329.1  1490.1  2515.9 1530.99  2692.9 1582.19  2784.6 1635.62  2846.9 1639.78
#Mann= 16 ,-1 , 0
       0     .12       0   457.8    .016       0   492.1     .12       0
  679.96     .03       0 1523.21     .08       0  1598.2    .016       0
  1637.5     .08       0  1674.2     .12       0  1742.8    .016       0
  1772.7     .08       0  1807.9     .12       0  1899.4    .016       0
  1929.2     .12       0  1994.8     .06       0    2102    .016       0
  2515.9     .12       0
#Block Obstruct= 2 ,-1
 1978.74 2035.391479.672 2821.05  2846.91654.291
Bank Sta=679.96,1523.21
XS Rating Curve= 0 ,0
Exp/Cntr=0.5,0.3

Type RM Length L Ch R = 1 ,10450.6 ,299,304.8,304
BEGIN DESCRIPTION:
Merged DS Survey NEW012BU
END DESCRIPTION:
XS GIS Cut Line= 3
     1997896.015      244301.645     1999680.737      245079.423
     2001069.626      244516.923
#Sta/Elev= 30
       0 1755.62    42.6  1746.6    85.2 1725.37   403.1  1485.3   541.8  1419.2
   570.3 1417.49   616.2 1395.55     626 1387.57   632.6 1371.37   759.5 1353.72
  1329.9 1348.22 1719.27 1353.55  1766.5    1380  1805.7 1381.42  1843.8 1390.45
  1855.1 1420.75  1861.6 1427.71  2005.7 1445.89    2301 1457.19  2353.4 1458.64
  2523.7 1458.73  2596.8 1462.53  2718.9 1469.76  2771.2  1473.9  2974.8 1505.89
  3121.6 1536.91  3216.5  1556.1  3278.6 1573.32  3337.1  1586.2  3445.3 1645.03
#Mann= 17 ,-1 , 0
       0     .12       0   541.8    .016       0   570.3     .12       0
   759.5     .04       0 1719.27     .12       0  1805.7     .08       0
  2005.7    .016       0    2301     .12       0  2353.4     .08       0
  2523.7    .016       0  2596.8     .08       0  2718.9    .016       0
  2771.2     .12       0  2974.8    .016       0  3121.6     .12       0
  3216.5    .016       0  3278.6     .12       0
#XS Ineff= 2 , 0
             500 1418.04    1940          1418.3
Permanent Ineff=
       F       F
#Block Obstruct= 12 ,-1
 1944.31 1944.591455.295 1963.49 1991.581457.389 2066.45 2092.161463.451
 2136.85 2160.091468.768 2171.06 2199.421470.551 2221.55  2224.2 1471.96
 2332.96 2446.321473.697 2619.37 2656.351479.398 2663.75 2723.181481.616
 2828.46  2881.8 1495.11 2965.23 2992.871518.085 3149.19 3199.571558.264
Bank Sta=759.5,1719.27
XS Rating Curve= 0 ,0
Exp/Cntr=0.5,0.3

Type RM Length L Ch R = 3 ,10329   ,,,
BEGIN DESCRIPTION:
Hinton Bypass. Modeled using survey data: Merged US Survey NEW010RP.
END DESCRIPTION:
Bridge Culvert--1,0,-1,-1, 0
Deck Dist Width WeirC Skew NumUp NumDn MinLoCord MaxHiCord MaxSubmerge Is_Ogee
92,52,2.6,0, 60, 60, , , , 0, ,,,
       0    32.8    62.3    75.4    88.5   150.8   229.4     236   245.8   265.5
   304.8   337.6   363.8   393.3   406.4   435.9   445.7   488.4   511.3  531.73
     565   565.1 1285.88 1849.85    1852  1852.1  1953.4  1986.2  2032.1  2064.9
  2163.2  2294.4  2369.8    2537  2602.6  2684.6  2720.7  2825.6  2881.3  2894.4
  2930.5  3097.7  3127.2  3137.1  3143.6  3166.6  3179.7  3209.2  3238.7  3284.6
  3297.8  3333.8  3353.5  3369.9  3379.7  3402.7    3406  3415.8  3432.2  3445.3
  1694.8  1695.3 1692.39 1690.07 1684.24 1643.26 1583.34 1577.28 1564.46 1548.27
 1521.37 1496.31  1479.3 1462.98 1454.13 1439.05 1432.26 1428.01 1413.07  1412.3
 1412.94 1418.54 1418.37 1424.62 1424.62 1421.82 1427.02 1439.78 1443.32 1443.46
 1449.07  1449.4 1456.47 1458.77 1463.38 1466.28 1470.56 1472.55 1477.79 1480.43
 1482.51 1512.12  1518.9 1519.44 1523.57 1524.29 1527.96 1531.66 1538.17 1543.34
 1549.72 1557.45 1566.92 1571.71 1577.36 1580.23 1581.61 1591.11 1602.02 1605.85
                                                                                
                                                                                
         1403.54 1403.37 1409.62 1409.62
                                                                                
                                                                                
                                                                                
    -2.9    13.5    75.8   154.4     161   167.5   170.8   190.5   229.8   262.6
   285.5   318.3   331.4   360.9   370.7   390.4   413.4   416.6     433   439.6
     490   490.1 1210.88 1774.85    1777  1777.1  1878.4  1911.2  1957.1  1989.9
  2088.2  2219.4  2294.8    2462  2527.6  2609.6  2645.7  2750.6  2806.3  2819.4
  2855.5  3022.7  3052.2  3062.1  3068.6  3091.6  3104.7  3134.2  3163.7  3206.4
  3222.8  3258.8  3278.5  3294.9  3304.7  3327.7    3331  3347.4  3363.8  3445.3
 1690.85 1684.24 1643.26 1583.34 1577.28 1567.72 1564.46 1548.27 1521.37 1496.31
 1481.35 1462.98 1454.13 1439.05 1432.26 1429.21 1428.01 1426.88 1414.54 1412.73
 1412.94 1415.74 1421.17 1427.42 1427.42 1424.62 1429.82 1442.58 1446.12 1443.46
 1449.07  1449.4 1456.47 1458.77 1463.38 1466.28 1470.56 1472.55 1477.79 1480.43
 1482.51 1512.12  1518.9 1519.44 1523.57 1524.29 1527.96 1531.66 1538.17 1542.59
 1549.72 1557.45 1566.92 1571.71 1577.36 1580.23 1581.61 1595.86 1604.72    1616
                                                                                
                                                                                
         1400.74 1406.17 1412.42 1412.42
                                                                                
                                                                                
                                                                                
Pier Skew, UpSta & Num, DnSta & Num=  ,747.16, 2 ,669.68, 2 , 0 , 0 , 0 ,,
       4       4
    1300    1411
       4       4
    1300    1411
Pier Skew, UpSta & Num, DnSta & Num=  ,930.08, 2 ,855.24, 2 , 0 , 0 , 0 ,,
       4       4
    1300    1411
       4       4
    1300    1411
Pier Skew, UpSta & Num, DnSta & Num=  ,1113.25, 2 ,1038.51, 2 , 0 , 0 , 0 ,,
       4       4
    1300    1411
       4       4
    1300    1411
Pier Skew, UpSta & Num, DnSta & Num=  ,1250.9, 2 ,1221.15, 2 , 0 , 0 , 0 ,,
       4       4
    1300    1411
       4       4
    1300    1411
Pier Skew, UpSta & Num, DnSta & Num=  ,1431.35, 2 ,1406.68, 2 , 0 , 0 , 0 ,,
       4       4
    1300    1411
       4       4
    1300    1411
Pier Skew, UpSta & Num, DnSta & Num=  ,1615.04, 2 ,1589.37, 2 , 0 , 0 , 0 ,,
       4       4
    1300    1411
       4       4
    1300    1411
BR Coef=-1 , 1 , 0 ,, 0 ,,,0.8,-1,1.2,0,
WSPro=,,,, 1 ,,,, 0 ,,,, 0 ,,,,-1 ,-1 ,-1 , 0 , 0 , 0 , 0 , 0
BC Design=,, 0 ,, 0 ,,0,,,,
BC HTab HWMax=0
BC HTab TWMax=0
BC HTab MaxFlow=0
BC Use User HTab Curves=0
BC User HTab FreeFlow(D)= 0

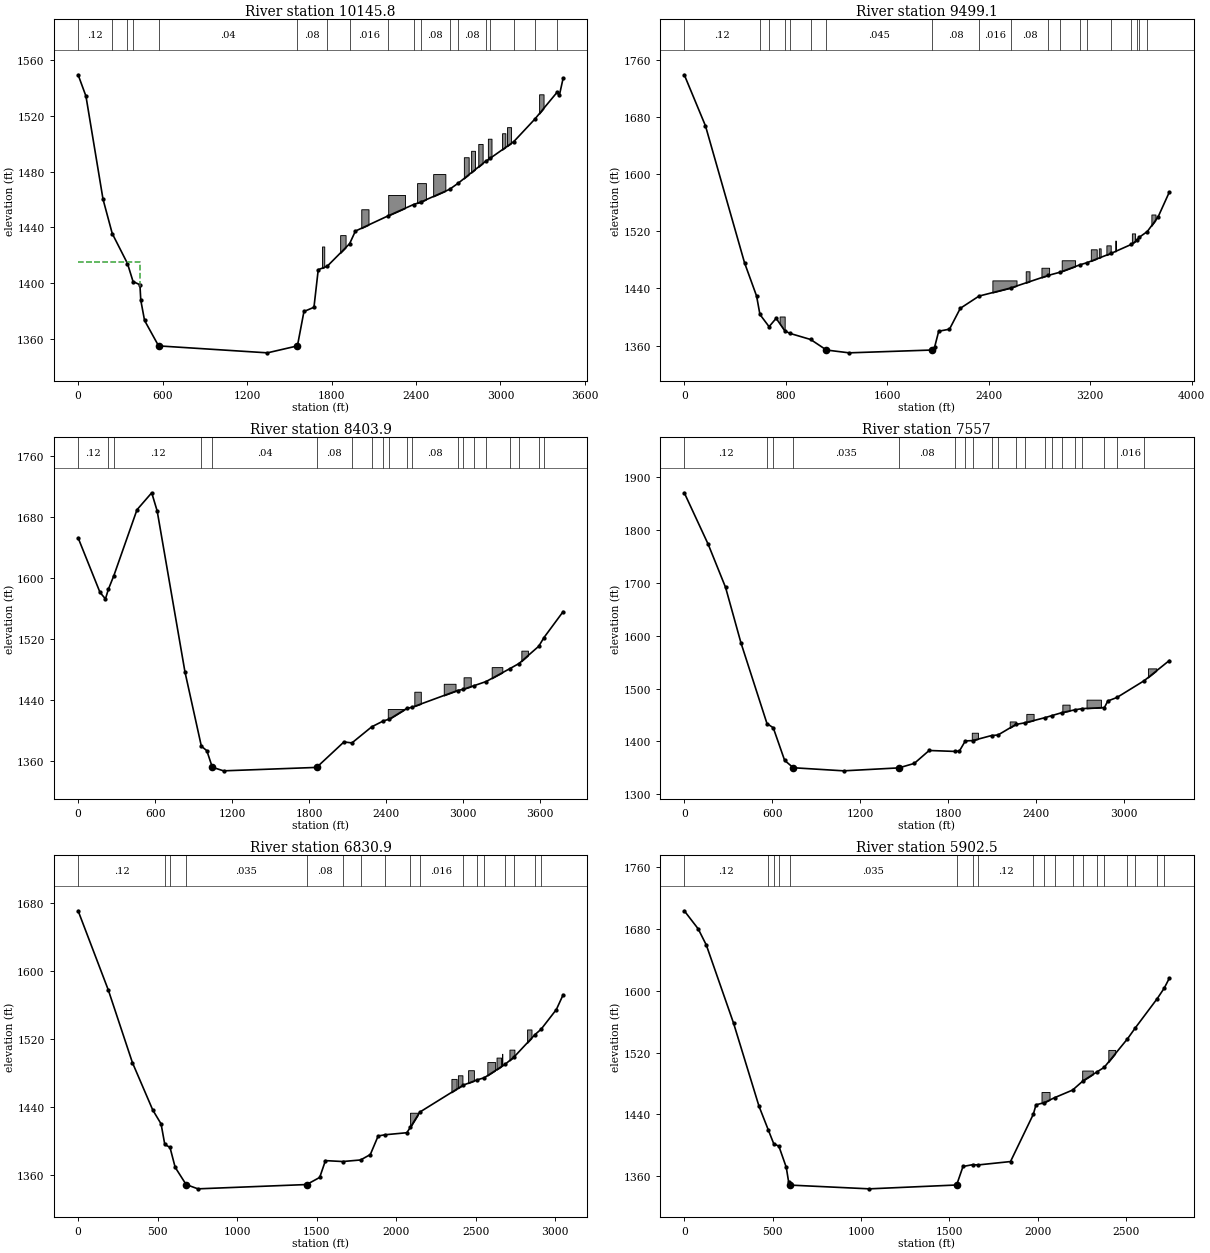
Type RM Length L Ch R = 1 ,10145.8 ,925.4,646.7,359.5
BEGIN DESCRIPTION:
Merged US Survey NEW008BD
END DESCRIPTION:
XS GIS Cut Line= 3
     1998034.904      244669.701     1999819.626      245447.478
     2001208.515      244884.978
#Sta/Elev= 30
       0  1549.6    55.7 1534.25     177 1460.16   242.5 1435.51   350.7 1413.98
   390.3 1401.02   439.2  1398.7   445.2 1387.62     472 1373.06   571.8 1354.77
  1344.9 1349.78  1557.9 1354.77  1604.3 1379.49  1675.4 1382.52  1705.8 1409.53
  1769.8 1412.03  1928.8 1428.23  1969.8 1437.28  2202.6 1448.24  2382.9 1456.37
  2435.4 1458.17  2638.7 1467.29    2701 1471.76  2894.4  1487.4  2927.2 1489.59
  3095.1 1501.59  3243.7 1517.67  3402.7 1537.05  3419.1 1535.04  3445.3 1547.08
#Mann= 18 ,-1 , 0
       0     .12       0   242.5     .06       0   350.7    .016       0
   390.3     .12       0   571.8     .04       0  1557.9     .08       0
  1769.8     .06       0  1928.8    .016       0  2202.6     .08       0
  2382.9    .016       0  2435.4     .08       0  2638.7    .016       0
    2701     .08       0  2894.4    .016       0  2927.2     .12       0
  3095.1    .016       0  3243.7     .06       0  3402.7     .12       0
#XS Ineff= 2 , 0
             440    1415    1810            1415
Permanent Ineff=
       F       F
#Block Obstruct= 13 ,-1
 1732.74 1748.431426.206 1861.46 1900.021434.376 2011.43 2062.821452.956
 2202.53 2322.191463.236 2407.94 2470.661471.744 2522.13 2608.661478.251
 2740.25 2774.331490.346 2791.69 2819.13 1494.96 2842.66 2873.461499.897
  2910.9 2936.511503.658 3011.63 3035.051507.579 3046.84 3075.481511.964
 3274.69 3306.21 1535.57
Bank Sta=571.8,1557.9
XS Rating Curve= 0 ,0
Exp/Cntr=0.5,0.3

Type RM Length L Ch R = 1 ,9499.1  ,1348.3,1095.2,800
XS GIS Cut Line= 3
     1997585.251      246008.242     1999850.876      245591.576
     2001239.765      244975.256
#Sta/Elev= 30
       0 1739.56   167.1 1667.97   475.1 1476.01   570.2  1429.3   596.4 1403.59
   668.5 1386.44   724.2  1398.2     793 1380.43   835.6  1376.9   996.2 1368.48
  1120.7 1353.71  1299.4 1349.78    1953 1353.72  1972.7 1357.29  2005.4 1380.04
  2090.6 1382.96  2175.8 1412.19  2323.3 1429.34  2572.2 1440.65  2870.2 1458.38
  2961.8  1462.8  3115.8 1472.99  3174.7 1476.17  3364.6 1489.21  3525.1 1501.88
  3567.7 1507.46  3584.1 1511.47  3649.6  1519.8  3734.7 1540.23  3823.1 1574.99
#Mann= 19 ,-1 , 0
       0     .12       0   596.4    .016       0   668.5     .12       0
     793    .016       0   835.6     .06       0   996.2    .016       0
  1120.7    .045       0    1953     .08       0  2323.3    .016       0
  2572.2     .08       0  2870.2    .016       0  2961.8     .08       0
  3115.8    .016       0  3174.7     .12       0  3364.6    .016       0
  3525.1     .08       0  3567.7     .12       0  3584.1    .016       0
  3649.6     .12       0
#Block Obstruct= 11 ,-1
  751.57  791.471400.735 2428.72 2618.91 1451.33 2691.53 2721.281464.089
 2815.54 2875.721469.045 2975.22 3080.431479.536 3204.62 3250.981494.899
 3267.65 3281.961496.239  3327.4 3361.361500.452 3396.76 3402.721507.019
 3528.29 3553.461517.182 3682.08 3714.281543.715
Bank Sta=1120.7,1953
XS Rating Curve= 0 ,0
Exp/Cntr=0.3,0.1

Type RM Length L Ch R = 1 ,8403.9  ,1006.8,846.9,670.6
XS GIS Cut Line= 3
     1998488.029      247744.353     2000441.154      245739.145
     2001248.446      245183.589
#Sta/Elev= 30
       0 1652.83   170.4 1581.22     213 1572.54     236  1585.3   278.6 1603.18
   458.9 1689.66   573.6 1711.94   616.2 1687.97   832.6 1476.79   960.4 1379.19
    1003  1373.3  1045.6 1351.62    1133 1346.85  1858.5 1351.35  2071.5 1384.78
  2133.8 1383.52  2287.9 1404.65  2379.6 1412.46  2425.5 1414.76  2559.9 1428.72
  2599.3 1430.19  2956.5 1452.32  2999.1 1453.83  3087.6 1458.81  3179.4 1464.11
  3362.9 1480.92    3435 1487.72  3589.1 1510.39  3630.4 1521.92  3779.2 1555.87
#Mann= 20 ,-1 , 0
       0     .12       0     236    .016       0   278.6     .12       0
   960.4    .016       0  1045.6     .04       0  1858.5     .08       0
  2133.8    .016       0  2287.9     .06       0  2379.6    .016       0
  2425.5     .08       0  2559.9    .016       0  2599.3     .08       0
  2956.5    .016       0  2999.1     .08       0  3087.6    .016       0
  3179.4     .08       0  3362.9    .016       0    3435     .12       0
  3589.1    .016       0  3630.4     .12       0
#Block Obstruct= 6 ,-1
 2413.11  2543.11428.045 2619.84  2670.31450.713 2849.21 2940.811461.155
  3003.6 3059.381469.675 3222.71 3305.42 1483.03 3453.74 3504.911504.644
Bank Sta=1045.6,1858.5
XS Rating Curve= 0 ,0
Exp/Cntr=0.3,0.1

Type RM Length L Ch R = 1 ,7557    ,746.9,726.1,701.6
XS GIS Cut Line= 3
     1999833.515      248204.423     2000640.807      245904.076
     2001352.612      245400.603
#Sta/Elev= 30
       0 1870.86   163.8 1772.88   281.8 1691.59   386.7 1586.63   564.5 1433.51
   607.3 1425.58   684.8 1363.88   743.8 1349.87  1087.8    1344  1464.7 1349.61
  1569.6 1358.07  1671.1 1382.57  1845.9 1380.79  1877.6 1381.56    1918  1400.7
  1967.6 1401.29  2097.7 1410.94  2140.8 1411.87  2262.4 1431.86    2325 1435.03
    2463 1444.86    2508  1448.6  2578.7 1454.42  2668.1 1459.74  2716.3 1461.93
  2867.2 1463.89  2890.2 1476.34  2952.8 1483.03    3138 1514.72  3309.8 1552.96
#Mann= 20 ,-1 , 0
       0     .12       0   564.5    .016       0   607.3     .12       0
   743.8    .035       0  1464.7     .08       0  1845.9     .12       0
    1918    .016       0  1967.6     .06       0  2097.7    .016       0
  2140.8     .08       0  2262.4    .016       0    2325     .08       0
    2463    .016       0    2508     .08       0  2578.7     .06       0
  2668.1    .016       0  2716.3     .08       0  2867.2     .12       0
  2952.8    .016       0    3138     .12       0
#Block Obstruct= 6 ,-1
 1962.05 2004.071416.208 2220.91 2262.781437.588 2334.34  2383.8 1451.92
 2580.09 2629.491469.418 2745.08  2843.3 1478.86 3164.15 3221.291538.129
Bank Sta=743.8,1464.7
XS Rating Curve= 0 ,0
Exp/Cntr=0.3,0.1

Type RM Length L Ch R = 1 ,6830.9  ,905.8,928.4,960
Node Name=S
XS GIS Cut Line= 3
     2000597.404      248395.395     2001222.404      246216.576
     2001656.432      245565.534
#Sta/Elev= 30
       0 1671.37   190.3 1577.79   341.2  1492.6   469.1 1436.75   521.6  1420.3
     545 1396.03   577.6 1392.64   610.1  1369.2     679 1348.86   753.3 1343.79
  1436.8 1348.85  1518.8 1357.23  1554.9 1377.04  1663.5 1375.96  1775.8  1377.8
    1837 1384.18  1886.2 1406.03  1928.8 1407.48  2066.6  1409.9  2088.1  1416.1
  2147.7 1434.15  2420.6 1465.91  2510.1 1472.26  2552.6 1474.59  2686.5 1490.83
  2741.4 1499.28  2872.4 1525.53  2910.5 1531.77  3006.6 1555.04  3049.1 1572.38
#Mann= 17 ,-1 , 0
       0     .12       0     545    .016       0   577.6     .12       0
     679    .035       0  1436.8     .08       0  1663.5    .016       0
  1775.8     .12       0  1928.8     .06       0  2088.1     .06       0
  2147.7    .016       0  2420.6     .08       0  2510.1    .016       0
  2552.6     .12       0  2686.5    .016       0  2741.4     .06       0
  2872.4    .016       0  2910.5     .12       0
#Block Obstruct= 9 ,-1
 2087.07 2135.781433.445 2346.91 2379.47  1473.3 2387.67 2416.061477.553
 2451.69 2488.221483.547 2572.62 2621.741493.118 2630.58 2658.721498.418
 2664.66 2666.971502.845 2711.65  2742.91507.792 2822.51 2850.281531.544
Bank Sta=679,1436.8
XS Rating Curve= 0 ,0
Exp/Cntr=0.3,0.1

Type RM Length L Ch R = 1 ,5902.5  ,927.5,1037.9,1136.9
XS GIS Cut Line= 2
     2001441.154      248615.881     2002336.987      246022.131
#Sta/Elev= 30
       0 1703.67    78.7 1680.26   124.6 1659.33   278.7 1558.15   422.9 1450.32
     475 1419.88   506.2 1401.76   535.3 1398.57     577 1371.28   590.1 1352.71
     600 1348.16  1047.1 1343.32  1540.9  1348.3    1577  1372.3  1631.3 1374.61
  1662.5 1374.29  1845.8 1378.68  1974.8 1439.96    1990 1452.18  2037.5 1455.07
  2094.7 1461.42    2197 1471.32  2257.1 1483.45  2334.1 1494.75  2375.7 1500.73
  2507.5 1537.69  2552.7 1552.16    2676 1589.86  2715.4 1603.36  2744.1 1616.21
#Mann= 19 ,-1 , 0
       0     .12       0     475     .06       0   506.2    .016       0
   535.3     .12       0     600    .035       0  1540.9     .08       0
  1631.3    .016       0  1662.5     .12       0  1974.8    .016       0
  2037.5     .08       0  2094.7    .016       0    2197     .12       0
  2257.1     .08       0  2334.1    .016       0  2375.7     .12       0
  2507.5    .016       0  2552.7     .12       0    2676    .016       0
  2715.4     .12       0
#Block Obstruct= 3 ,-1
 2021.21 2066.69 1468.79 2251.21 2311.481496.625 2399.19 2437.911523.335
Bank Sta=600,1540.9
XS Rating Curve= 0 ,0
Exp/Cntr=0.3,0.1