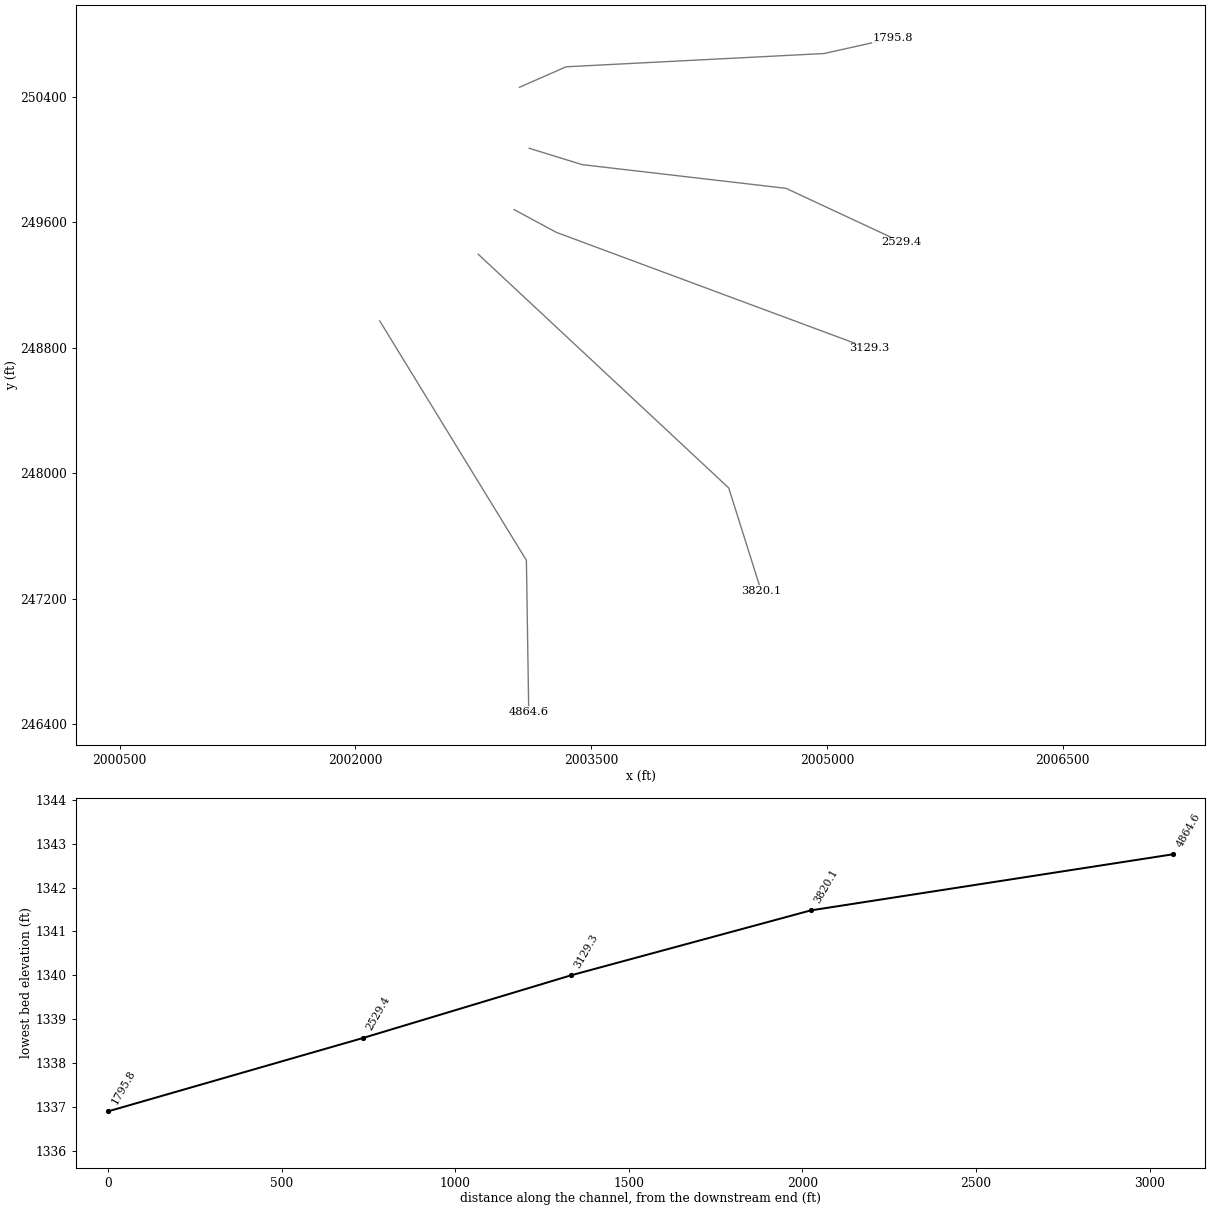
HEC-RAS study NEWRV2_AE.prj: NEWRV2_AE

--- NEWRV2_AE.g01 (geometry) --- (continued)

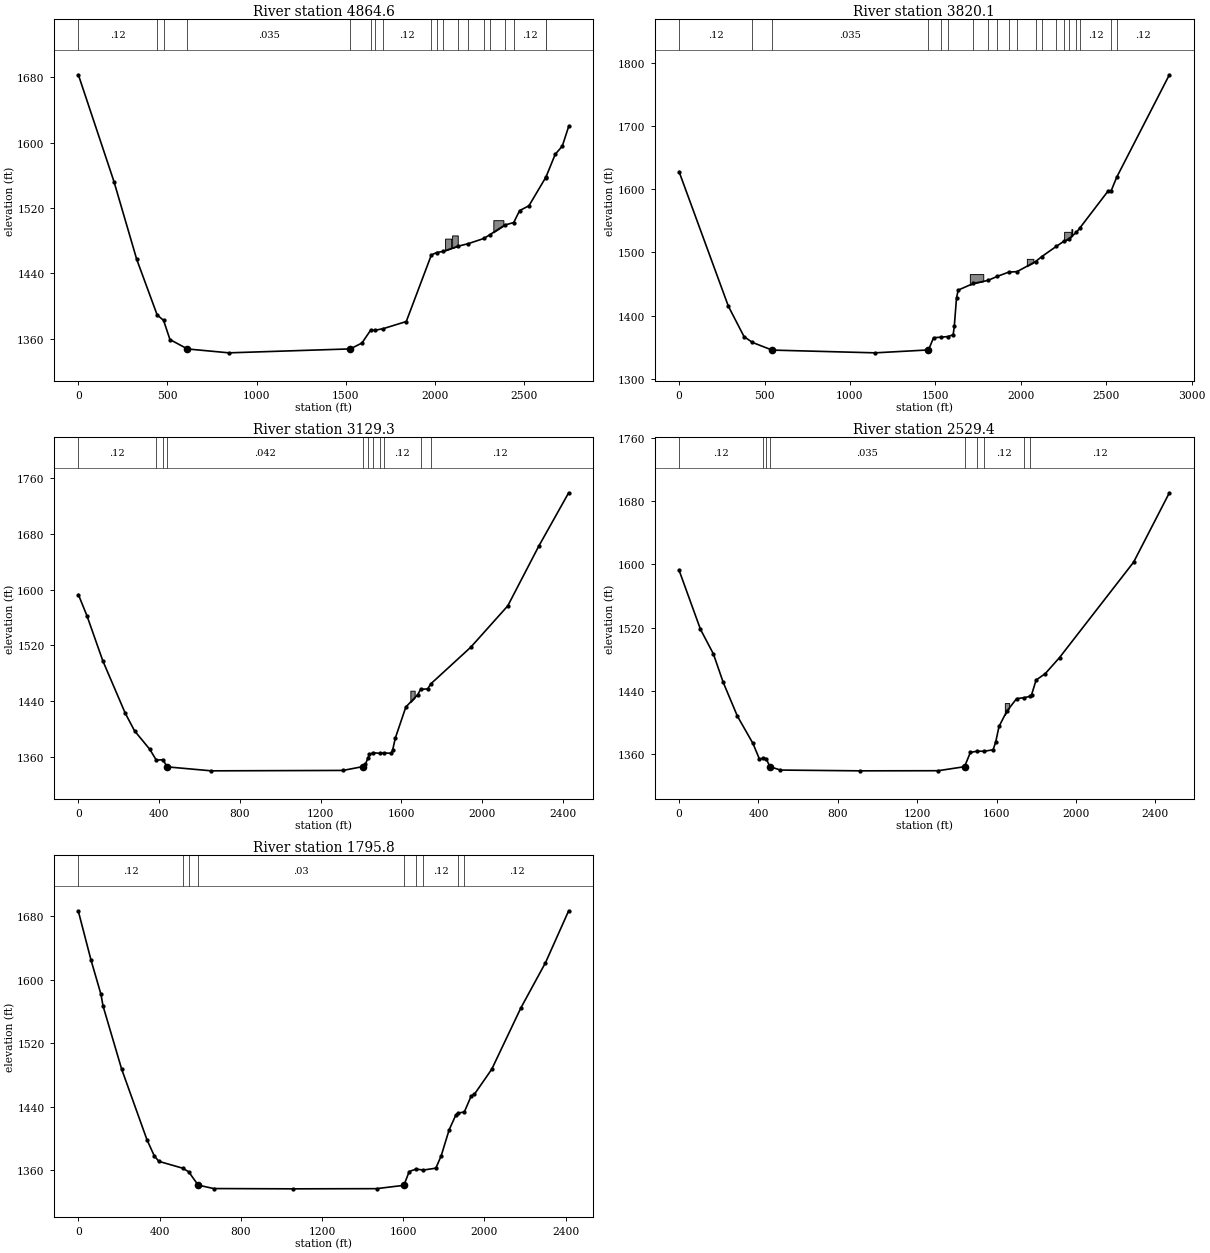
Type RM Length L Ch R = 1 ,4864.6  ,912.6,1044.5,1169.7
XS GIS Cut Line= 3
     2002154.695      248970.048     2003087.767      247444.474
     2003102.612      246480.464
#Sta/Elev= 30
       0  1683.1   199.8 1552.45   327.5 1457.22   442.2 1389.21   478.2 1382.51
   514.2 1359.01   612.5 1347.51   845.4 1342.76  1526.3 1347.58  1591.8 1354.76
  1640.9 1370.57  1667.1 1370.43  1711.8  1372.4  1840.8  1381.1  1981.6 1462.57
  2011.1 1465.51  2047.4 1466.92  2129.3 1473.14  2188.4 1476.36    2277 1482.81
  2309.7 1487.31  2393.6 1499.17  2443.9 1502.23    2477 1516.86  2529.4 1522.77
  2622.9 1557.19  2624.4 1557.62    2677  1585.8  2716.4  1595.7  2752.4 1619.81
#Mann= 19 ,-1 , 0
       0     .12       0   442.2    .016       0   478.2     .12       0
   612.5    .035       0  1526.3     .12       0  1640.9     .08       0
  1667.1    .016       0  1711.8     .12       0  1981.6     .08       0
  2011.1    .016       0  2047.4     .08       0  2129.3     .12       0
  2188.4    .016       0    2277     .12       0  2309.7     .08       0
  2393.6    .016       0  2443.9     .12       0  2622.9    .016       0
  2624.4     .12       0
#Block Obstruct= 3 ,-1
 2058.59 2092.541482.557 2098.12 2129.751486.476 2329.56 2385.79 1505.13
Bank Sta=612.5,1526.3
XS Rating Curve= 0 ,0
Exp/Cntr=0.3,0.1

Type RM Length L Ch R = 1 ,3820.1  ,526.2,690.8,886.7
Node Name=R
XS GIS Cut Line= 3
     2002781.432      249395.395     2004375.182      247905.812
     2004581.779      247249.562
#Sta/Elev= 30
       0 1627.58   288.7 1414.98   380.5    1367   429.7 1357.88   544.6 1345.82
    1147 1341.48  1459.8 1346.06  1489.3  1365.3    1532 1366.25  1574.6  1367.2
  1604.1 1370.09  1610.7 1383.09  1623.8 1428.44  1633.7 1440.57  1722.2 1451.04
  1807.5 1455.84  1863.3 1462.33  1929.4 1468.96  1978.1 1469.72  2086.4 1485.62
  2122.4 1493.41  2207.7 1509.62  2250.3 1517.33  2279.8  1521.1  2325.7 1531.86
  2345.3 1538.57  2512.4 1597.56  2528.8 1597.38  2561.5 1618.95  2869.5 1780.63
#Mann= 20 ,-1 , 0
       0     .12       0   429.7    .016       0   544.6    .035       0
  1459.8     .08       0    1532    .016       0  1574.6     .12       0
  1722.2     .08       0  1807.5    .016       0  1863.3     .06       0
  1929.4    .016       0  1978.1     .08       0  2086.4    .016       0
  2122.4     .12       0  2207.7    .016       0  2250.3     .08       0
  2279.8     .12       0  2325.7     .06       0  2345.3     .12       0
  2528.8    .016       0  2561.5     .12       0
#Block Obstruct= 4 ,-1
 1701.76 1780.261465.856 2035.44 2073.751489.925 2253.51 2292.761532.608
 2296.04 2301.321537.013
Bank Sta=544.6,1459.8
XS Rating Curve= 0 ,0
Exp/Cntr=0.3,0.1

Type RM Length L Ch R = 1 ,3129.3  ,494.8,600,724.7
XS GIS Cut Line= 3
     2003008.862      249680.117     2003279.696      249534.284
     2005267.543      248794.701
#Sta/Elev= 30
       0 1592.83    42.5 1562.52   121.1  1497.8   232.3 1422.59   278.2 1397.43
   353.5 1370.94   386.1 1355.33   419.5 1355.97   438.7 1345.74   658.4    1340
  1310.4 1340.59  1409.1 1346.08  1422.2 1349.38  1433.4 1358.06  1441.8 1363.47
  1459.6  1366.1  1494.3    1365  1515.2 1365.72    1550 1365.11  1556.6 1369.64
  1569.7 1386.81  1622.1 1431.58  1681.2 1449.35  1695.2 1456.95  1730.3 1457.53
  1744.7 1464.51  1943.4 1517.28    2127  1576.7    2281 1662.62  2428.6  1738.9
#Mann= 11 ,-1 , 0
       0     .12       0   386.1    .016       0   419.5     .12       0
   438.7    .042       0  1409.1     .08       0  1433.4     .12       0
  1459.6     .08       0  1494.3    .016       0  1515.2     .12       0
  1695.2    .016       0  1744.7     .12       0
#Block Obstruct= 1 ,-1
  1644.5 1665.661454.974
Bank Sta=438.7,1409.1
XS Rating Curve= 0 ,0
Exp/Cntr=0.3,0.1

Type RM Length L Ch R = 1 ,2529.4  ,650.3,733.5,822.8
XS GIS Cut Line= 4
     2003106.085      250070.742      2003442.89      249966.576
     2004739.765      249815.534     2005475.876      249471.784
#Sta/Elev= 30
       0 1592.55   107.7  1517.8     173 1486.55     222 1450.88   293.8 1407.86
   372.2 1373.29     405 1353.45   422.7 1354.47     439 1353.98   457.5 1343.87
   510.8 1339.55   912.1 1338.57  1305.8 1338.73  1438.4 1343.81  1467.9 1361.91
  1502.4 1363.46  1536.7 1363.33  1582.7 1365.24  1595.9  1375.5  1612.3  1394.8
  1651.6 1414.05  1700.8 1429.94  1739.6 1431.23  1769.1 1432.92  1776.1 1434.68
    1799 1453.48  1844.9 1461.55    1917 1481.91  2290.4 1602.73  2470.6 1690.56
#Mann= 9 ,-1 , 0
       0     .12       0   422.7    .016       0     439     .12       0
   457.5    .035       0  1438.4     .08       0  1502.4    .016       0
  1536.7     .12       0  1739.6    .016       0  1769.1     .12       0
#Block Obstruct= 1 ,-1
 1641.61 1663.431424.342
Bank Sta=457.5,1438.4
XS Rating Curve= 0 ,0
Exp/Cntr=0.3,0.1

Type RM Length L Ch R = 1 ,1795.8  ,712.7,859.5,1013.1
XS GIS Cut Line= 4
     2003043.585      250459.631     2003340.707      250590.238
     2004981.543      250674.692     2005418.585      250772.131
#Sta/Elev= 30
       0 1686.13    62.3 1624.77   111.5  1581.5   121.3 1567.24   213.1 1487.67
   337.7 1398.83   373.8 1378.45   396.7 1371.48   514.6 1362.83   543.6 1358.27
   590.2  1341.6   666.6 1337.26  1059.1  1336.9  1468.8 1337.12  1603.6 1341.34
  1629.8 1358.68  1663.1 1361.74  1699.8 1360.57    1761 1362.92  1787.2  1378.4
  1826.6 1411.23  1859.4 1429.76  1870.7  1432.2  1901.4 1433.68  1934.8 1453.56
  1951.2 1456.04  2036.2 1487.34    2180 1564.68    2301 1621.41  2415.3 1686.82
#Mann= 9 ,-1 , 0
       0     .12       0   514.6    .016       0   543.6     .12       0
   590.2     .03       0  1603.6     .08       0  1663.1    .016       0
  1699.8     .12       0  1870.7    .016       0  1901.4     .12       0
Bank Sta=590.2,1603.6
XS Rating Curve= 0 ,0
Exp/Cntr=0.3,0.1