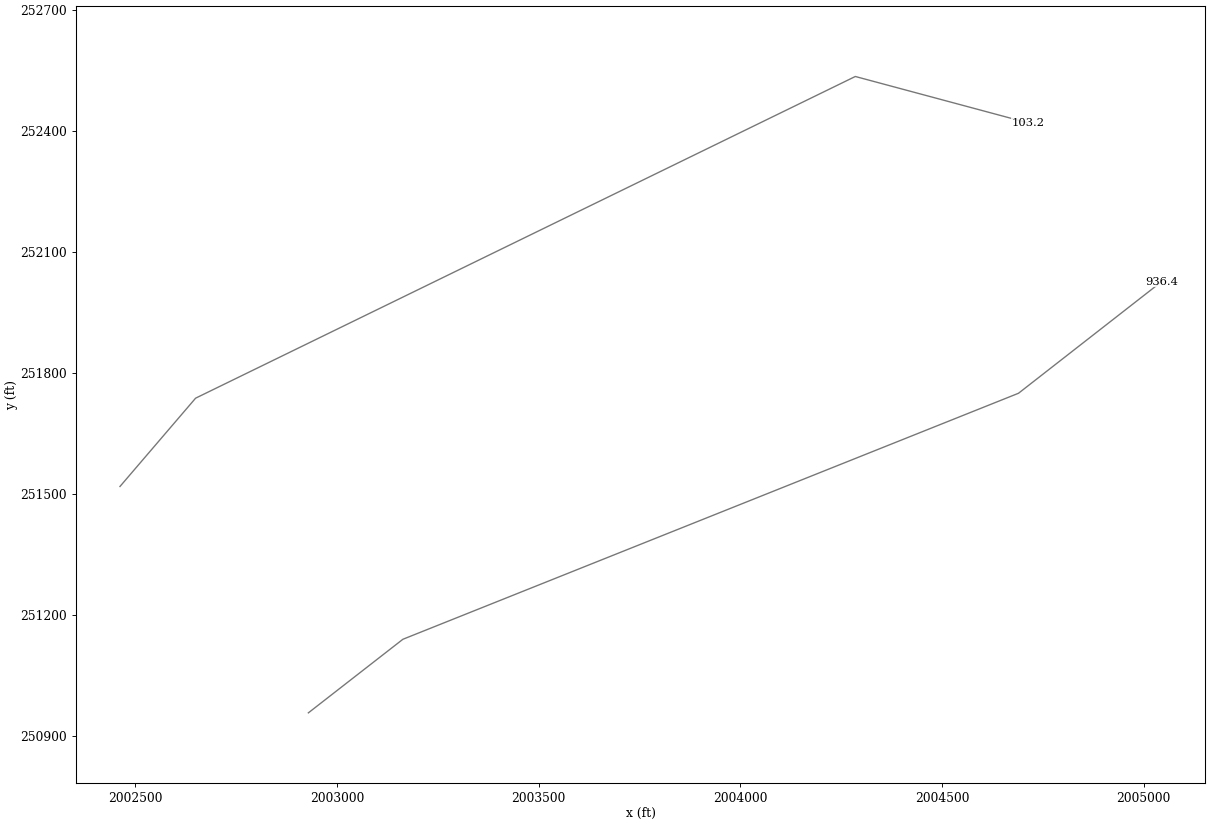
HEC-RAS study NEWRV2_AE.prj: NEWRV2_AE

--- NEWRV2_AE.g01 (geometry) --- (continued)

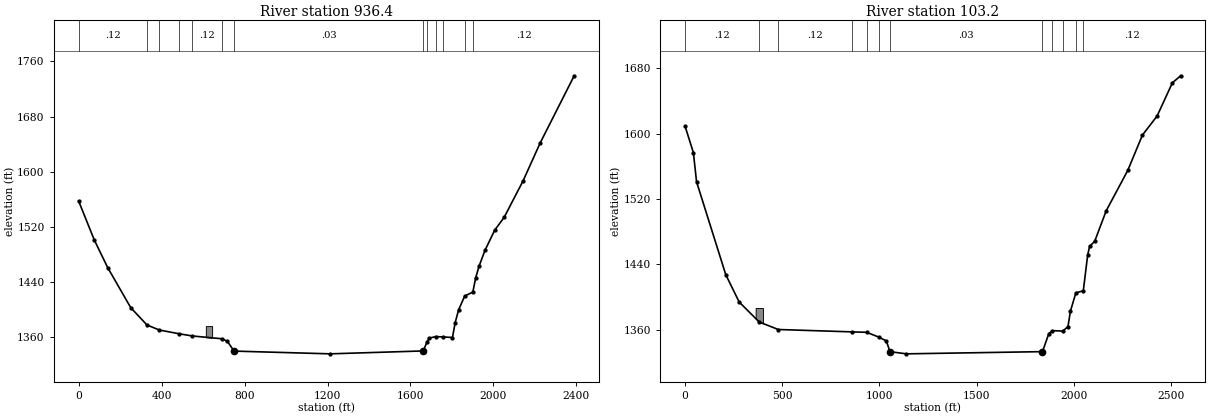
Type RM Length L Ch R = 1 ,936.4   ,809.6,833.1,864.5
XS GIS Cut Line= 4
     2002929.001      250957.895     2003163.376      251140.187
     2004689.418      251749.562     2005043.585      252025.604
#Sta/Elev= 30
       0 1557.29      75 1500.98   140.3  1460.4   251.2 1402.33   329.4 1377.16
   389.2  1369.8   483.6 1364.44   547.7 1361.17   689.5 1357.16   716.7 1353.55
   749.5 1339.19  1213.2 1335.21  1661.3 1339.42  1680.1 1352.71  1690.9 1358.15
    1722 1360.24  1757.4 1359.81  1802.4 1358.93  1815.5 1380.59  1831.9 1399.07
  1861.4 1419.22  1900.7 1424.95  1913.9 1445.14  1930.3 1462.33  1959.8 1485.98
  2005.7  1514.7  2051.6 1533.54  2143.3 1586.81  2225.3 1641.64  2389.2 1739.21
#Mann= 13 ,-1 , 0
       0     .12       0   329.4     .06       0   389.2     .12       0
   483.6     .06       0   547.7     .12       0   689.5    .016       0
   749.5     .03       0  1661.3     .12       0  1680.1     .08       0
    1722    .016       0  1757.4     .12       0  1861.4    .016       0
  1900.7     .12       0
#Block Obstruct= 1 ,-1
  613.33  643.611375.522
Bank Sta=749.5,1661.3
XS Rating Curve= 0 ,0
Exp/Cntr=0.3,0.1

Type RM Length L Ch R = 1 ,103.2   ,120.5,103.2,79.7
XS GIS Cut Line= 4
     2002461.987      251518.659     2002649.487      251737.409
     2004284.904      252534.284     2004711.987      252419.701
#Sta/Elev= 30
       0 1608.92    42.6 1576.75    58.9 1541.14   209.5 1427.35   278.3 1394.06
   381.2 1369.69   479.4 1360.48   860.7 1357.57   934.1 1357.06   995.6 1351.28
  1035.5 1346.52  1053.9 1333.39  1138.7 1330.73  1838.6 1333.42  1871.3 1355.42
  1890.2 1359.08  1943.4 1358.56  1969.7 1364.05  1982.8 1383.17  2010.3 1405.23
  2048.7 1407.87  2071.3 1451.66  2081.1  1462.1  2107.3 1468.28  2166.3 1505.52
  2277.7  1555.1    2353 1598.22  2428.3 1621.45    2507 1662.07  2549.5 1670.68
#Mann= 12 ,-1 , 0
       0     .12       0   381.2     .06       0   479.4     .12       0
   860.7     .06       0   934.1     .12       0   995.6    .016       0
  1053.9     .03       0  1838.6     .08       0  1890.2    .016       0
  1943.4     .12       0  2010.3    .016       0  2048.7     .12       0
#Block Obstruct= 1 ,-1
  362.96  400.591386.721
Bank Sta=1053.9,1838.6
XS Rating Curve= 0 ,0
Exp/Cntr=0.3,0.1
LCMann Table=0

Chan Stop Cuts=-1
Use User Specified Reach Order=0
Composite Channel Slope=5